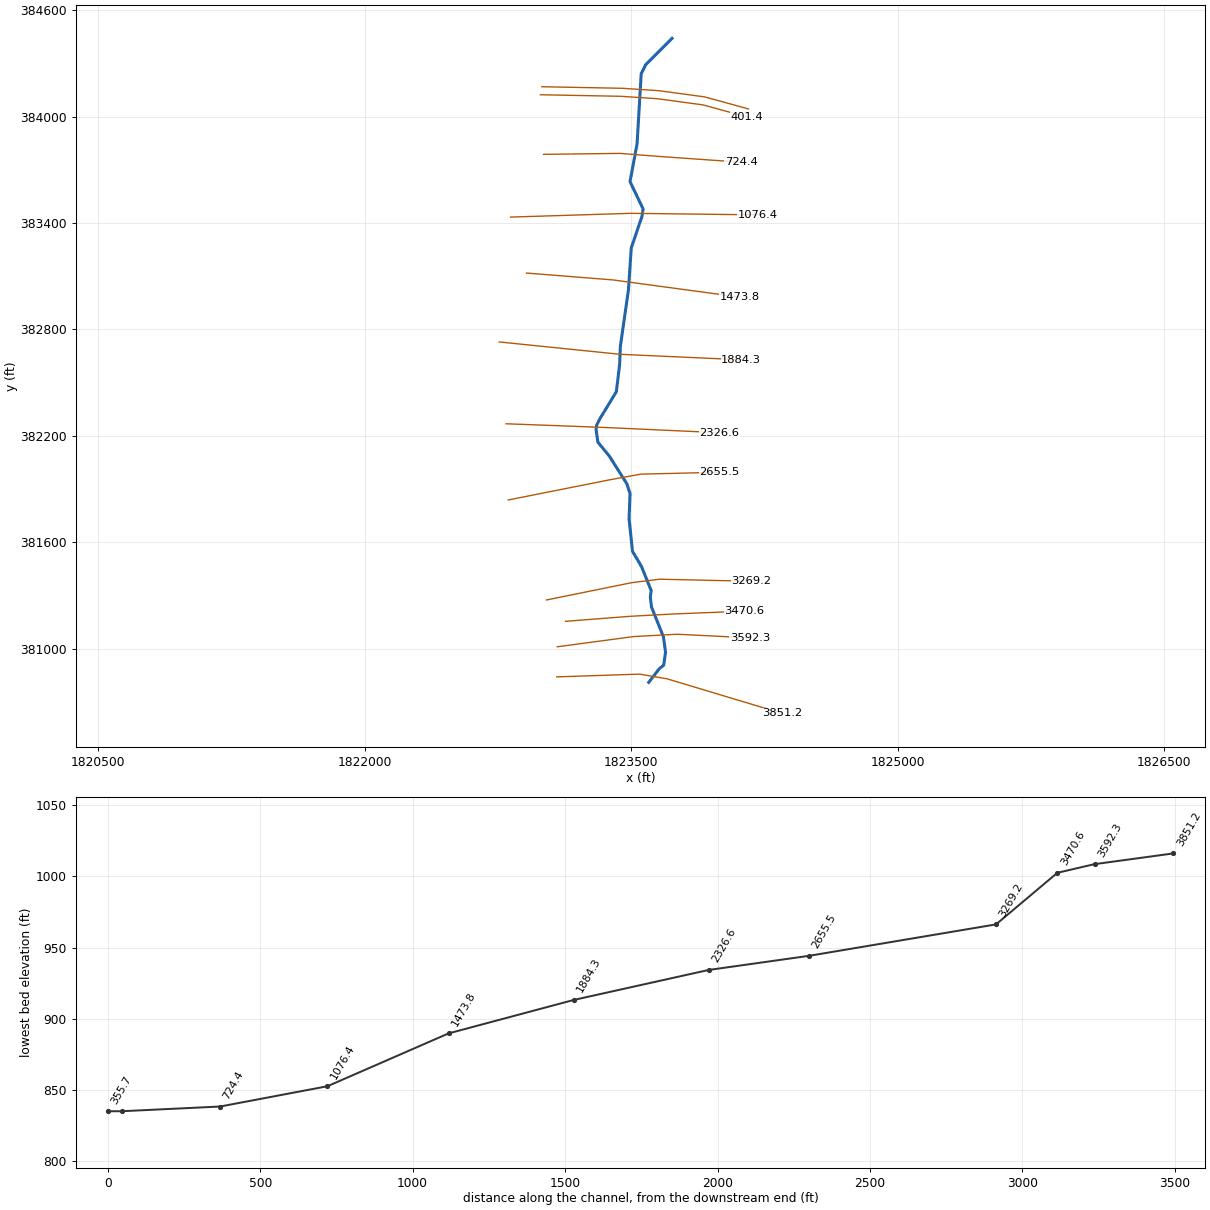
--- JoesRun.prj (project) ---

Proj Title=JoesRun
Current Plan=p01
Default Exp/Contr=0,0
English Units
Geom File=g01
Flow File=f01
Plan File=p01
BEGIN DESCRIPTION:
END DESCRIPTION:
DSS Export Rating Curves= 0
DSS Export Rating Curve Sorted= 0
DSS Export Volume Flow Curves= 0
DXF OffsetX= 0
DXF OffsetY= 0
DXF ScaleX= 0
DXF ScaleY= 0

--- JoesRun.p01 (plan) ---

Plan Title=Floodplain
Program Version=4.00
Geom File=g01
Flow File=f01
K Sum by GR=0
Std Step Tol=0.01
Critical Tol=0.01
Num of Std Step Trials=20
Max Error Tol=0.3
Flow Tol Ratio=0.001
Split Flow NTrial=30
Split Flow Tol=0.02
Split Flow Ratio=0.02
Log Output Level=0
Friction Slope Method=1
Unsteady Friction Slope Method=2
Unsteady Bridges Friction Slope Method=1
Global Log Level=0
CheckData=False
Run HTab=0
Run UNet=0
Run PostProcess=0
UNET Theta=0
UNET Theta Warmup=0
UNET ZTol=0
UNET ZSATol=0
UNET MxIter=0
UNET MaxInSteps=0
UNET DtIC=0
UNET DtMin=0
UNET MaxCRTS=0
UNET WFStab=0
UNET SFStab=0
UNET WFX=0
UNET SFX=0
UNET DSS MLevel=0
UNET DZMax Abort=0
UNET Convert EG Bridges=0
UNET Use Existing IB Tables=0
UNET Froude Limit=0
UNET Froude Power=0
Write IC File=0
Echo Input=False
Echo Output=False
Write Detailed=0

--- JoesRun.f01 (steady flow) ---

Flow Title=NFF Regression Equation
Program Version=4.10
Number of Profiles= 1
Profile Names=P100yr
River Rch & RM=JoesRun,Main            ,3851.2
     895
River Rch & RM=JoesRun,Main            ,3269.2
     904
River Rch & RM=JoesRun,Main            ,2655.5
     999
Boundary for River Rch & Prof#=JoesRun,Main            , 1
Up Type= 0
Dn Type= 3
Dn Slope=0.01017
DSS Import GetInterval= 0
DSS Import GetPeak= 0
DSS Import FillOption= 0

--- JoesRun.g01 (geometry) ---

Geom Title=USGS 10m DEM
Program Version=4.10

River Reach=JoesRun         ,Main
Reach XY= 30
     1823599.151      380809.679     1823658.807       380886.88
     1823683.371       380906.18     1823693.898      380979.873
     1823681.616      381067.601     1823614.942      381234.285
     1823608.168      381289.676     1823613.188      381327.278
     1823558.796      381462.379     1823507.913      381548.354
     1823488.613      381730.829     1823493.877      381874.704
     1823476.331      381928.394     1823378.075       382084.55
     1823313.156      382163.506     1823302.629      382235.444
     1823306.138      382260.008     1823323.683      382295.099
     1823416.676      382447.747      1823435.17      382599.342
     1823439.485      382704.616     1823485.104      383023.948
     1823500.895      383259.061     1823560.551      383434.869
     1823567.569      383478.733     1823493.877      383633.135
     1823533.594      383845.438     1823556.842      384241.194
     1823582.805       384293.12     1823730.442      384440.756

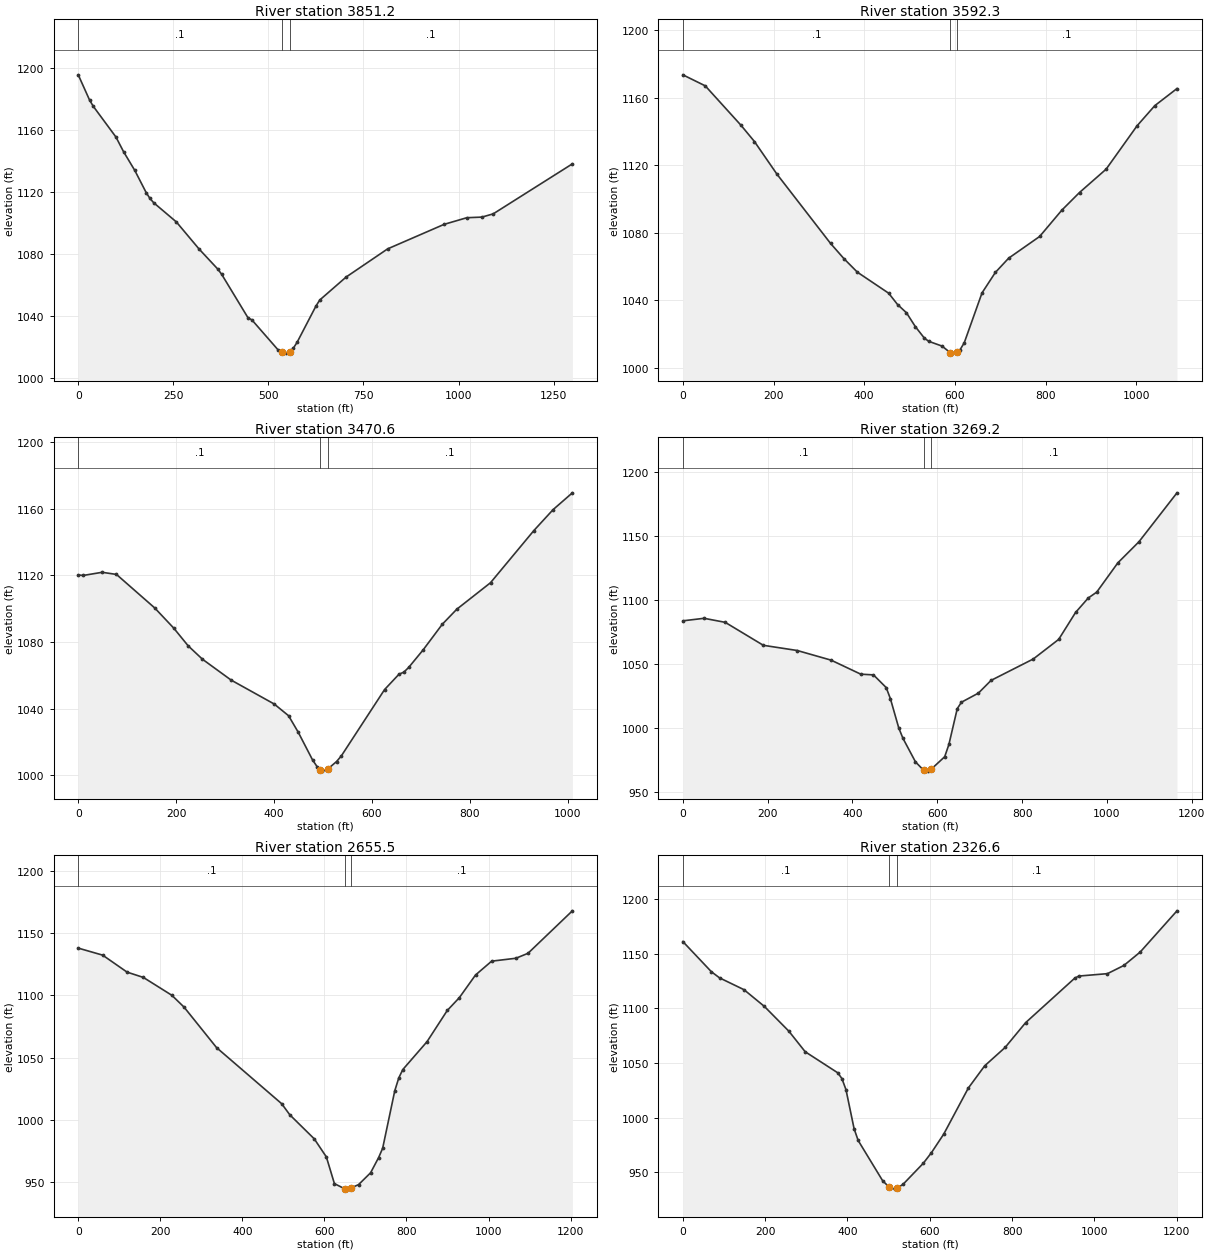
Type RM Length L Ch R = 1 ,3851.2  ,254.5,258.8,263.2
XS GIS Cut Line= 4
       1823081.5      380840.561     1823547.646      380856.186
     1823704.186      380829.225      1824349.73      380634.832
#Sta/Elev= 30
       0 1195.67    29.8 1179.38    39.7 1175.31    99.2 1155.52   119.1 1146.11
   148.8 1133.96   178.6 1119.72   188.6 1115.92   198.5 1113.14     258 1100.78
   317.6 1083.35   367.2  1070.3   377.1 1067.01   446.6 1038.87   456.5 1037.64
     526 1018.11   535.9  1016.8   545.8 1016.16   555.8 1016.98   565.7 1019.39
   575.6 1023.18   625.2 1046.58   635.2 1050.45   704.6 1065.27   813.6 1083.41
   962.3 1099.24  1021.8  1103.5  1061.5  1103.9  1091.2 1105.99  1299.4 1138.25
#Mann= 3 , 0 , 0
       0      .1       0   535.9    .045       0   555.8      .1       0
Bank Sta=535.9,555.8
XS Rating Curve= 0 ,0
Exp/Cntr=0.3,0.1

Type RM Length L Ch R = 1 ,3592.3  ,121.6,121.8,122
XS GIS Cut Line= 4
     1823084.481      381010.266     1823514.949      381067.991
     1823759.741      381081.012      1824169.55      381060.613
#Sta/Elev= 30
       0 1173.66    49.4 1167.13   128.3 1143.72   157.9  1134.1   207.3 1114.83
   325.7 1073.69   355.4  1064.6     385  1056.6   453.9 1044.16   473.5 1037.45
   493.2 1032.54   512.8 1024.31   532.4  1017.6   542.2 1015.63   571.6  1012.8
   589.6 1008.93   591.2 1008.62   604.6 1009.29   610.8 1010.38   620.6 1014.76
   659.8 1044.34   689.2 1056.47   718.5 1064.92   786.9  1077.8   835.8  1093.4
   874.8 1103.87   933.5 1117.71  1001.8 1143.45  1040.9 1155.39  1089.8 1165.52
#Mann= 3 , 0 , 0
       0      .1       0   589.6    .045       0   604.6      .1       0
Bank Sta=589.6,604.6
XS Rating Curve= 0 ,0
Exp/Cntr=0.3,0.1

Type RM Length L Ch R = 1 ,3470.6  ,199.5,201.4,203.3
XS GIS Cut Line= 4
     1823131.269      381153.929     1823501.061      381182.575
     1823745.852      381195.595     1824139.081       381211.22
#Sta/Elev= 30
       0 1120.18     9.8 1119.85    48.8 1121.76    78.1 1120.48   156.2  1100.4
   195.2 1088.26   224.5  1077.7   253.8 1069.64   312.3 1057.15   400.3 1042.81
   429.7 1035.78   449.3 1025.97   478.8 1009.24   488.6 1004.98   494.5 1003.52
   498.4 1002.56   509.5 1003.76   527.8 1008.31   537.6 1011.72   625.9 1051.46
   655.4 1060.68   665.2 1061.89   675.1 1064.71   704.6 1075.22   743.9 1090.64
   773.4 1099.62   842.3  1115.5   930.9 1146.78   970.2 1159.33  1009.6  1169.4
#Mann= 3 , 0 , 0
       0      .1       0   494.5    .045       0   509.5      .1       0
Bank Sta=494.5,509.5
XS Rating Curve= 0 ,0
Exp/Cntr=0.3,0.1

Type RM Length L Ch R = 1 ,3269.2  ,612.9,613.6,614.4
XS GIS Cut Line= 4
     1823023.717      381274.154     1823503.375      381371.811
      1823659.72      381391.313     1824177.855      381379.623
#Sta/Elev= 30
       0 1083.81      50 1085.79    99.9 1082.63   189.8 1064.68   269.7 1060.62
   349.6 1053.08   419.6 1042.11   449.5 1041.56   479.5 1031.66   489.5 1022.88
   509.2 1000.04     519     992   548.6  973.55   568.3  966.85   578.1  966.33
   585.2  967.69   617.5  977.59   627.4  987.17   647.1 1015.18     657 1020.19
   696.9 1027.29   726.8 1037.25   826.5 1054.01   886.3 1069.31   926.1 1090.35
     956 1101.65     976 1106.25  1025.8 1129.13  1075.6 1145.62  1165.3 1183.87
#Mann= 3 , 0 , 0
       0      .1       0   568.3    .045       0   585.2      .1       0
Bank Sta=568.3,585.2
XS Rating Curve= 0 ,0
Exp/Cntr=0.3,0.1

Type RM Length L Ch R = 1 ,2655.5  ,333.7,328.9,324.1
XS GIS Cut Line= 4
     1822808.063      381837.957     1823381.878      381952.141
     1823555.459       381983.79     1823998.167      381994.207
#Sta/Elev= 30
       0 1137.97    59.5 1132.32     119 1118.67   158.7 1114.41   228.1 1100.06
   257.8 1090.57   337.2 1057.96   495.8 1012.91   515.6    1004   575.2  984.67
   604.7  970.14   624.3  948.69   649.1  944.57   653.7  944.26   664.1  945.12
   683.1  947.85   712.5   957.4   732.1  969.64   741.9   977.1   771.4 1023.28
   781.2 1033.65     791 1040.36   850.1  1062.8   899.3 1087.83   928.8 1098.15
   968.2 1116.35  1007.5 1127.48  1066.6 1129.82  1096.1 1133.79  1204.3 1167.94
#Mann= 3 , 0 , 0
       0      .1       0   649.1    .045       0   664.1      .1       0
Bank Sta=649.1,664.1
XS Rating Curve= 0 ,0
Exp/Cntr=0.3,0.1

Type RM Length L Ch R = 1 ,2326.6  ,443.7,442.3,442.3
XS GIS Cut Line= 4
     1822796.199      382267.644     1823261.477      382250.283
     1823389.949      382245.075     1823995.852      382217.297
#Sta/Elev= 30
       0 1161.34    69.3 1133.67    89.2 1128.04   148.6  1117.2   198.1 1101.86
   257.6 1079.15   297.2 1060.33   376.4    1041   386.4 1035.76   396.3 1025.66
   416.1  989.74     426  978.94   485.4  942.08   501.2  936.23     515  934.35
  519.51  934.98   534.8  938.68   584.3  958.08   604.1  967.81     634  984.86
   693.6 1026.98   733.4  1047.4   783.1 1064.25   832.8 1086.94   952.1 1127.73
   962.1  1129.7  1031.7 1131.91  1071.5 1139.39  1111.2 1151.68  1200.7 1189.51
#Mann= 3 , 0 , 0
       0      .1       0   501.2    .045       0  519.51      .1       0
Bank Sta=501.2,519.51
XS Rating Curve= 0 ,0
Exp/Cntr=0.3,0.1

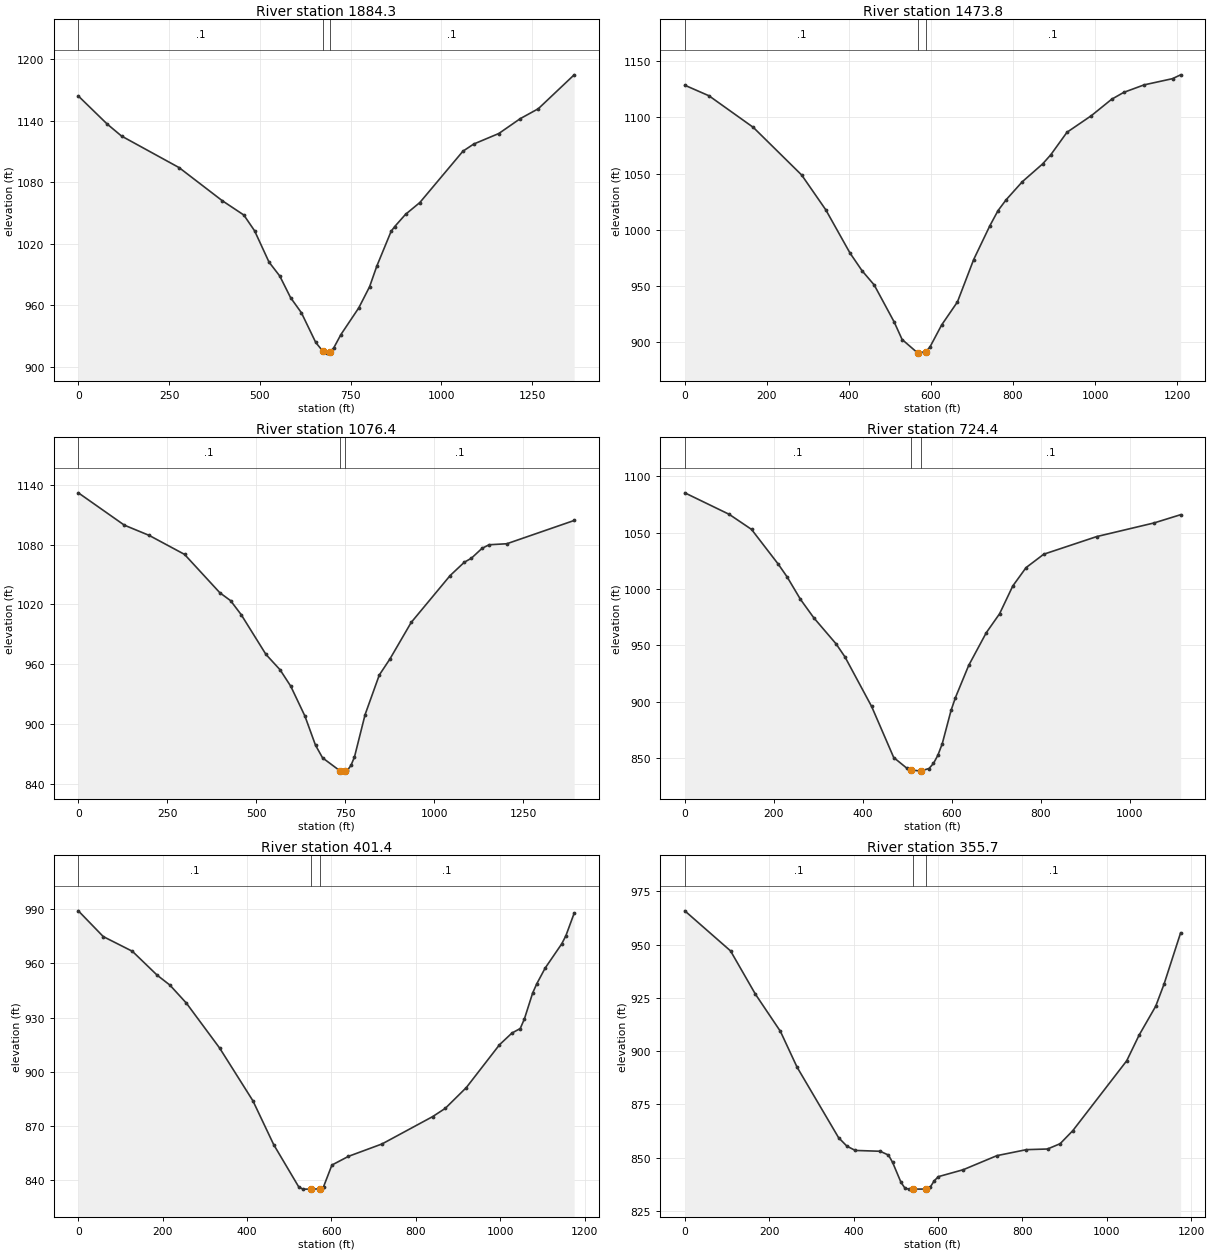
Type RM Length L Ch R = 1 ,1884.3  ,411.2,410.5,408.4
XS GIS Cut Line= 3
     1822757.228       382728.97      1823437.63      382659.357
     1824119.189      382628.654
#Sta/Elev= 30
       0 1164.24    79.3 1136.92     119 1125.16   277.6 1094.36   396.5 1062.08
     456 1048.09   485.7 1032.66   525.4 1002.15   555.1  988.53   584.8  967.48
   614.6  952.74   654.2  923.71     674  915.04     684  913.31   693.8  914.76
   703.7  918.38   723.5  931.43   772.9  957.58   802.6  978.18   822.4  998.21
   861.9 1032.21   871.8 1036.83   901.5 1048.72     941 1060.26  1059.7 1110.35
  1089.4 1117.34  1158.6 1127.63  1217.9 1142.18  1267.3 1151.78  1366.2 1184.89
#Mann= 3 , 0 , 0
       0      .1       0     674    .045       0   693.8      .1       0
Bank Sta=674,693.8
XS Rating Curve= 0 ,0
Exp/Cntr=0.3,0.1

Type RM Length L Ch R = 1 ,1473.8  ,394.6,397.4,400.2
XS GIS Cut Line= 4
     1822910.783       383117.47     1823400.366      383078.408
     1823572.241       383054.97     1824111.304      382982.054
#Sta/Elev= 30
       0 1128.71    58.9  1119.3     167 1091.12   284.9 1048.64   343.8 1017.54
   402.7  979.07   432.2  963.26   461.7  950.61   510.4  917.58   529.7  901.99
  567.88  889.93   568.2  889.84   587.5  891.24   597.2  895.04   626.1  914.97
   664.6  935.52   704.2  973.32   743.7 1003.49   763.5 1016.91   783.3 1026.59
   822.8  1042.7   872.3 1058.57   892.1  1066.7   931.6 1086.76     991 1101.56
  1040.4 1116.18  1070.1 1122.36  1119.6 1129.02  1188.8 1134.56  1208.6 1137.98
#Mann= 3 , 0 , 0
       0      .1       0  567.88    .045       0   587.5      .1       0
Bank Sta=567.88,587.5
XS Rating Curve= 0 ,0
Exp/Cntr=0.3,0.1

Type RM Length L Ch R = 1 ,1076.4  ,353.3,352,350.8
XS GIS Cut Line= 3
     1822820.974      383432.954     1823497.309      383454.125
     1824214.372      383445.582
#Sta/Elev= 30
       0    1132   129.4 1099.55     199 1089.31   298.5 1070.24     398 1031.67
   427.9 1023.84   457.7 1009.81   527.4  969.87   567.2  954.39   597.1  937.96
   636.9  908.03   666.7  878.75   686.6  866.05   735.4  853.06   746.4  852.74
   750.4  853.08   756.4   853.6   766.3   858.4   776.3     867   806.1  909.46
     846  949.18   875.9  965.27   935.6  1001.9  1045.2 1049.01    1085 1062.34
  1104.9 1066.38  1134.8 1076.28  1154.7 1079.89  1204.5  1080.9  1393.8 1104.26
#Mann= 3 , 0 , 0
       0      .1       0   735.4    .045       0   750.4      .1       0
Bank Sta=735.4,750.4
XS Rating Curve= 0 ,0
Exp/Cntr=0.3,0.1

Type RM Length L Ch R = 1 ,724.4   ,322.8,323,323.3
XS GIS Cut Line= 4
     1823007.137      383786.741     1823436.824       383791.95
     1823673.804       383773.72     1824119.116       383742.47
#Sta/Elev= 30
       0  1085.5    99.9 1066.38   149.9 1053.04   209.9 1022.23   229.8 1010.91
   259.8  990.98   289.8  974.57   339.8  951.47   359.8  939.87   419.7  895.87
   469.3  850.57     499  841.03     508  839.73   528.8   838.5  530.19  838.66
   548.6  840.83   558.5  845.28   568.4   852.5   578.3  862.78   598.1  892.39
     608  903.84   637.7  932.31   677.3   961.4   707.1  978.16   736.8 1002.85
   766.6 1019.13   806.3 1031.01   925.3 1046.67  1054.3 1058.79  1113.8 1066.09
#Mann= 3 , 0 , 0
       0      .1       0     508    .045       0  530.19      .1       0
Bank Sta=508,530.19
XS Rating Curve= 0 ,0
Exp/Cntr=0.3,0.1

Type RM Length L Ch R = 1 ,401.4   ,45.6,45.6,45.6
XS GIS Cut Line= 5
     1822988.908      384122.679     1823442.033      384113.998
     1823648.414      384100.326     1823905.574      384065.387
     1824152.102      383997.679
#Sta/Elev= 30
       0  989.08    59.1  974.84   128.1  966.71   187.2  953.42   216.8  948.07
   256.2  938.02     335  913.17   413.8  884.03   463.1  859.77   522.2   836.5
     532  835.19   551.7  835.19  572.49  835.34   581.2   836.5     601   848.5
   640.3  853.32   719.9  860.18   839.7  875.28   869.7  879.85   919.6  891.34
   998.2  915.02  1027.7  921.49  1047.4  923.99  1057.2  929.27  1076.9  943.68
  1086.7  948.79  1106.4   957.4  1145.7  970.81  1155.6  975.31  1175.2  987.75
#Mann= 3 , 0 , 0
       0      .1       0   551.7    .045       0  572.49      .1       0
Bank Sta=551.7,572.49
XS Rating Curve= 0 ,0
Exp/Cntr=0.3,0.1

Type RM Length L Ch R = 1 ,355.7   ,372.1,355.7,339.4
XS GIS Cut Line= 5
     1822997.588      384167.818     1823450.713      384159.137
     1823657.095      384145.465     1823914.255      384110.526
     1824160.783      384042.818
#Sta/Elev= 30
       0  965.88   108.4  947.07   167.5   926.7   226.6  909.29     266   892.5
   364.5  859.35   384.2  855.38     404  853.36   463.1  852.97   482.8  851.17
   492.6  847.72   512.3  838.42   522.2  835.54     532  835.19   541.8  835.19
   571.4  835.23   581.2  835.96   591.1  839.07     601  841.05     660  844.31
   739.9  850.92   809.8  853.73   859.7  854.03   889.6  856.52   919.6  862.64
  1047.4  895.46  1076.9  907.55  1116.2   921.1  1135.9  931.46  1175.2  955.55
#Mann= 3 , 0 , 0
       0      .1       0   541.8    .045       0   571.4      .1       0
Bank Sta=541.8,571.4
XS Rating Curve= 0 ,0
Exp/Cntr=0.3,0.1

Chan Stop Cuts=-1
Use User Specified Reach Order=0
Composite Channel Slope=5